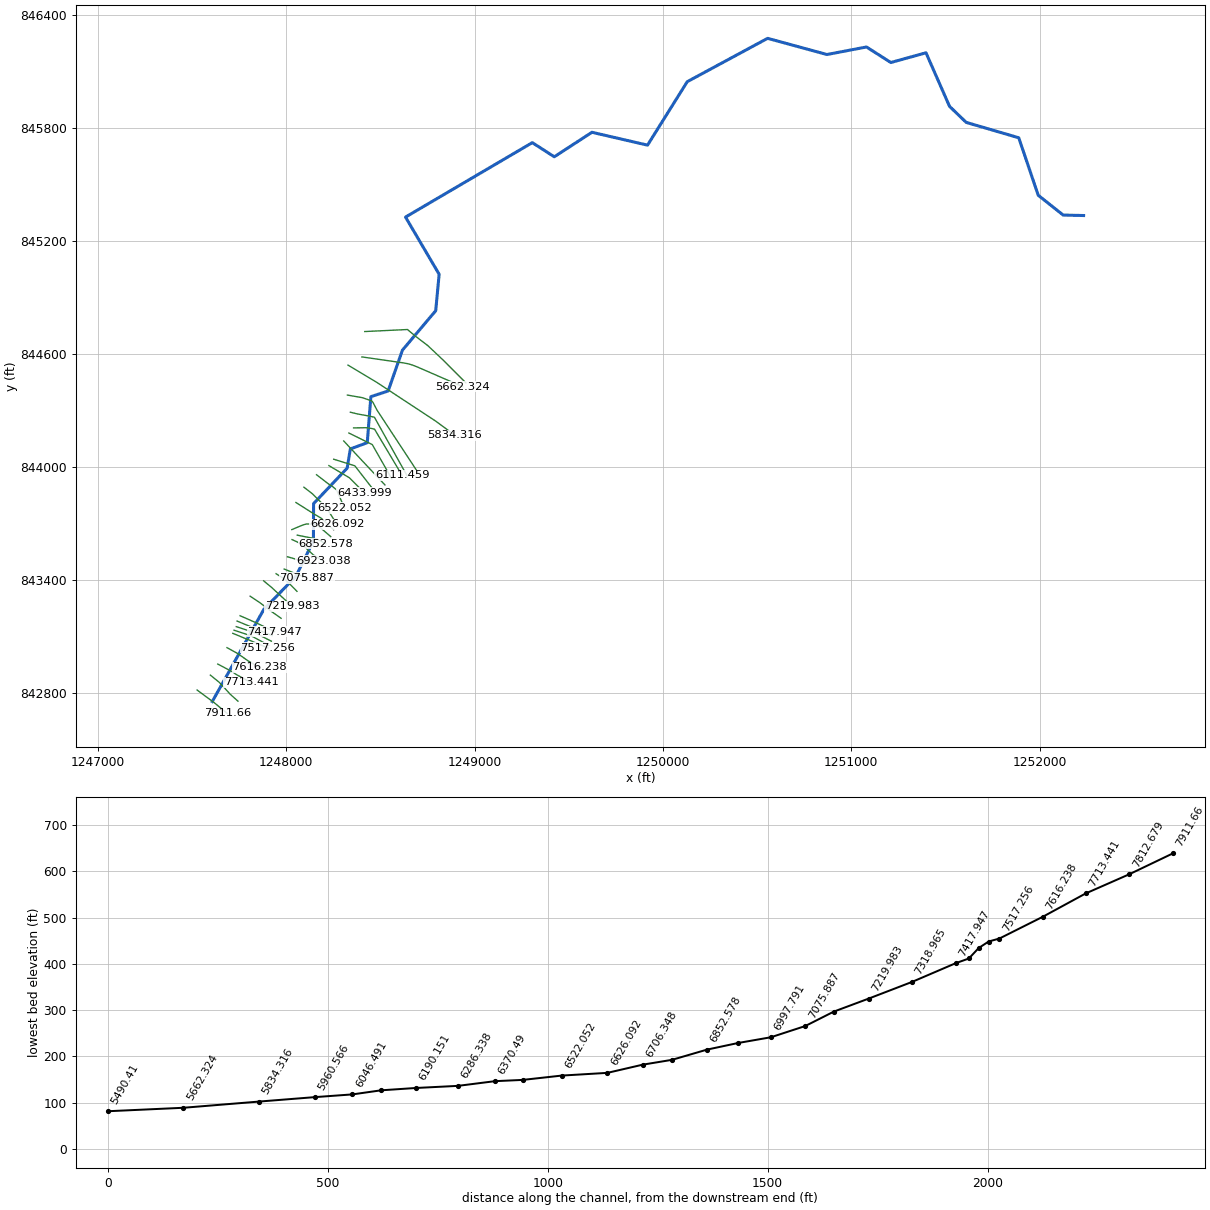
--- 123_ras.prj (project) ---

Proj Title=123
Current Plan=p01
Default Exp/Contr=0.3,0.1
English Units
Geom File=g01
Flow File=f01
Plan File=p01
Y Axis Title=Elevation
X Axis Title(PF)=Main Channel Distance
X Axis Title(XS)=Station
BEGIN DESCRIPTION:
RFD model 123 exported to HEC-RAS
END DESCRIPTION:

--- 123_ras.p01 (plan) ---

Plan Title=Plan 01
Program Version=4.10
Short Identifier=Plan 01
Geom File=g01
Flow File=f01
Subcritical Flow
Calc Critical at every XS
Secant Critical Depth

--- 123_ras.f01 (steady flow) ---

Flow Title=Flow 01
Program Version=5.01
Number of Profiles= 5
Profile Names=10yr,25yr,50yr,100yr,500yr
River Rch & RM=123,40, 7911.66
   95.54  168.96  239.05  322.17   562.4
River Rch & RM=123,40,7616.238
   99.92  176.89  250.51  337.95  591.57
River Rch & RM=123,40,7517.256
  106.18  188.22  266.88  360.54  633.44
River Rch & RM=123,40,7417.947
   109.3  193.88  275.08  371.86  654.47
River Rch & RM=123,40,7318.965
  112.42  199.54  283.28  383.18  675.56
River Rch & RM=123,40,7219.983
  118.66  210.85  299.68  405.87   717.9
River Rch & RM=123,40,7075.887
   119.9  213.12  302.96  410.41   726.4
River Rch & RM=123,40,6997.791
  121.15  215.38  306.24  414.95   734.9
River Rch & RM=123,40,6923.038
  143.51  256.07   365.4  497.02  889.34
River Rch & RM=123,40,6773.113
  147.22  262.85  375.28  510.74  915.32
River Rch & RM=123,40,6626.092
  150.94  269.63  385.15  524.48  941.36
River Rch & RM=123,40,6522.052
  247.29  446.56  644.54  887.56 1641.54
River Rch & RM=123,40,6433.999
  249.73  451.06  651.17  896.89 1659.78
River Rch & RM=123,40,6286.338
  252.16  455.55   657.8  906.22 1678.04
River Rch & RM=123,40,6190.151
  267.38  483.67  699.26  964.61 1792.54
River Rch & RM=123,40,6046.491
  269.21  487.04  704.23  971.63 1806.32
River Rch & RM=123,40,5960.566
  275.89  499.41  722.48  997.37 1856.93
River Rch & RM=123,40,5834.316
  489.61   897.5 1314.13 1837.83 3543.06
River Rch & RM=123,40,5662.324
  759.56  1405.8 2077.47 2934.42 5810.04
River Rch & RM=123,40, 5490.41
  764.28 1414.72 2090.92 2953.84  5850.7
River Rch & RM=123,40,5318.496
  768.41 1422.53  2102.7 2970.84  5886.3
River Rch & RM=123,40,5229.136
     769 1423.65 2104.38 2973.27 5891.38
River Rch & RM=123,40,5073.346
  793.74 1470.48 2175.06 3075.34 6105.37
River Rch & RM=123,40,5003.415
  796.69 1476.06 2183.48  3087.5 6130.88
River Rch & RM=123,40,4847.113
  798.46  1479.4 2188.53  3094.8  6146.2
Boundary for River Rch & Prof#=123,40,1
Up Type= 0
Dn Type= 2
Boundary for River Rch & Prof#=123,40,2
Up Type= 0
Dn Type= 2
Boundary for River Rch & Prof#=123,40,2
Up Type= 0
Dn Type= 2
Boundary for River Rch & Prof#=123,40,2
Up Type= 0
Dn Type= 2
Boundary for River Rch & Prof#=123,40,2
Up Type= 0
Dn Type= 2

--- 123_ras.g01 (geometry) ---

Geom Title=123
Program Version=4.10

River Reach=123,40
Reach XY= 30
1247607.73469017842757.3744344651247881.06795757 843245.70761553
1248051.23338622843421.2156493981248144.56669764843608.715591272
1248145.40003655 843807.048865981248323.73332305843995.382138451
1248340.39998779844097.0487745761248430.39996234844130.382095442
1248449.56663054844374.5486894121248541.23327118844404.548677863
 1248617.0665886844621.2152782781248793.73320952844830.381877977
1248812.06654314845023.7151536761248633.50958806845327.162111434
1249306.59864895845722.0193914731249423.26527915845647.019410213
1249623.26522423845777.0193659271249918.26513561845708.686044145
1250129.09841691846045.3526051561250555.76496505846275.352524714
1250870.76487003846189.5192075061251080.76480953846229.519189524
1251209.93143585846147.0192101031251396.59804921846198.685856035
1251521.59800417845914.5192696481251609.93130907845829.519292182
1251889.09789136845747.8526414441251992.43118539845442.852728545
 1252124.9311434845337.8527556561252233.26444485845335.352753206

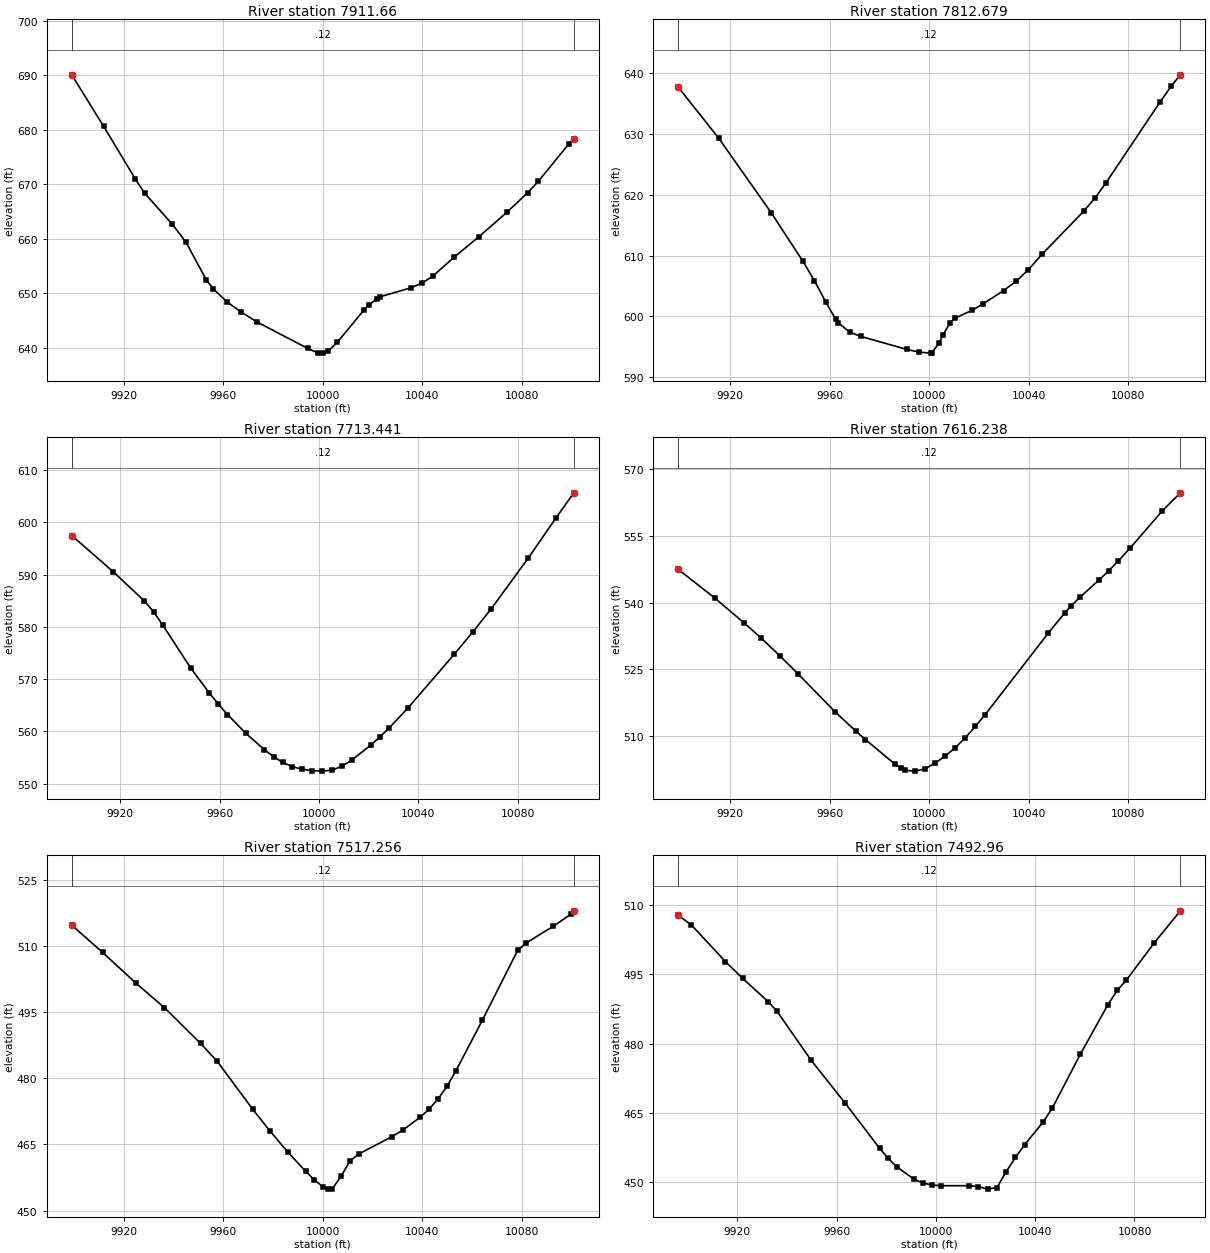
Type RM Length L Ch R = 1 , 7911.66,98.981800,98.981800,98.981800
XS GIS Cut Line= 5
1247527.05333592842818.1874877561247607.47717711 842758.76500522
1247609.12526092842757.6319475251247617.73496669842751.328648284
1247686.59286069842694.426870283
#Sta/Elev= 30
9899.005690.11099911.832680.66369924.627670.95969928.395668.35869939.437662.6993
9944.957659.39849953.181652.45489955.999650.8171 9961.52648.41839967.041646.6303
9973.578644.74569993.974639.90379998.053639.053810000.22639.047210002.08639.3791
10005.81641.021310016.54646.947110018.66647.936410021.69648.980410022.91649.3647
10035.68 651.06910039.94651.907610044.19653.1515 10052.7656.597210062.89660.4368
10073.98664.8592 10082.5668.512810086.75670.576310098.94677.4191   10101678.3496
#Mann= 3 , 0 , 0
9899.005    0.12       09899.005    0.12       0   10101    0.12       0
#XS Ineff= 2 , 0
       0                               0
Bank Sta=9899.005,10101
Exp/Cntr=0.3,0.1

Type RM Length L Ch R = 1 ,7812.679,99.237200,99.237200,99.237200
XS GIS Cut Line= 6
 1247597.3140262842897.5786105951247643.43189105842860.090028282
1247671.21971918842830.607003796 1247672.6339327 842829.19279019
1247702.47597948842796.2471913031247743.88779991842759.274326347
#Sta/Elev= 30
9899.053637.66999915.397629.24899936.537616.98139949.221609.0339 9953.78605.8958
9958.486602.29629962.355599.54199963.424598.95439967.932597.4215 9972.44596.7104
9991.055594.56359995.839594.133510000.57593.9624   10001594.0368   10004 595.616
10005.44596.891610008.43598.980110010.32599.701510017.28601.012610021.71 602.071
10029.87604.235310034.99605.796210039.65607.583910045.45610.246810062.22 617.326
10066.62619.430410071.01621.903910092.92635.2944 10097.4637.883110100.97 639.701
#Mann= 3 , 0 , 0
9899.053    0.12       09899.053    0.12       010100.97    0.12       0
#XS Ineff= 2 , 0
       0                               0
Bank Sta=9899.053,10100.97
Exp/Cntr=0.3,0.1

Type RM Length L Ch R = 1 ,7713.441,97.203400,97.203400,97.203400
XS GIS Cut Line= 6
1247636.65392059842956.1020092791247713.69836905 842915.39170374
1247724.32241927842908.233295924 1247725.8337974842906.923434803
1247735.53386475842900.3415322161247813.09047798842858.252796742
#Sta/Elev= 30
9900.589597.4727 9917.16590.5919 9929.81 584.956 9933.52582.87479937.231580.3168
9948.363572.17399955.784567.42829959.495565.25879963.206563.23229970.627559.6253
9978.049556.50799981.759555.1688 9985.47554.05899989.277553.26259993.233 552.774
9997.189 552.512 10001.2552.407910005.28552.602110009.25553.340510013.21554.5308
10020.74557.338610024.47558.941410028.21560.662410035.67564.423910054.34574.7321
 10061.8578.987210069.27583.4538 10084.2593.1879 10095.4600.8965 10102.5605.6467
#Mann= 3 , 0 , 0
9900.589    0.12       09900.589    0.12       0 10102.5    0.12       0
#XS Ineff= 2 , 0
       0                               0
Bank Sta=9900.589,10102.5
Exp/Cntr=0.3,0.1

Type RM Length L Ch R = 1 ,7616.238,98.981800,98.981800,98.981800
XS GIS Cut Line= 6
1247685.77556978 843043.105390621247741.06691813843012.605633666
1247771.33752641842991.6652814731247772.86429894842990.373396946
1247795.45453742842974.4131042011247858.03755433842938.194236584
#Sta/Elev= 30
9899.047547.51059913.669 541.0949925.391535.52769932.184532.17199939.897 528.055
9947.391523.89869962.192515.40579970.369511.15279974.358509.18899986.326503.6043
9988.617502.71729990.316502.26639994.305 502.0979998.294502.623410002.44503.9387
10006.45505.504310010.47507.381810014.49   509.610018.51512.150910022.52514.8422
10047.92533.205910054.47537.686410056.98539.238910060.77541.324810068.36545.1476
10072.15547.176110075.94549.351610080.67552.229310093.77560.703110100.97564.7411
#Mann= 3 , 0 , 0
9899.047    0.12       09899.047    0.12       010100.97    0.12       0
#XS Ineff= 2 , 0
       0                               0
Bank Sta=9899.047,10100.97
Exp/Cntr=0.3,0.1

Type RM Length L Ch R = 1 ,7517.256,24.295900,24.295900,24.295900
XS GIS Cut Line= 4
1247716.62611157843119.0056380311247809.07061966843080.922497162
1247810.87634067843080.0626299451247903.17090432843041.641737881
#Sta/Elev= 30
9899.018 514.6889911.435508.5086 9924.97501.48219936.273496.0126 9950.81487.9109
9957.563483.81129971.756473.00519978.853467.98339985.949463.25739993.046458.9495
9996.594456.987310000.17455.367810002.22454.886610003.74454.9174 10007.3457.7507
10010.85461.2035 10014.4462.828710027.83466.790110032.17 468.25110039.28471.2235
10042.83473.044810046.39475.353710049.94478.191110053.44481.597510064.16493.1347
10078.37 508.97810081.92510.702810092.59514.398810099.69517.130910100.97517.9379
#Mann= 3 , 0 , 0
9899.018    0.12       09899.018    0.12       010100.97    0.12       0
#XS Ineff= 2 , 0
       0                               0
Bank Sta=9899.018,10100.97
Exp/Cntr=0.3,0.1

Type RM Length L Ch R = 1 , 7492.96,22.773500,22.773500,22.773500
XS GIS Cut Line= 4
1247723.13652823843135.5854991421247814.21195262843105.761291338
1247828.79528595843097.9487913381247907.96195262843055.240458005
#Sta/Elev= 30
9896.146507.74419901.375505.70889915.185497.73559922.089 494.1029932.446489.0455
9935.898487.03069949.707476.38639963.516467.04759977.325457.32479980.778455.1378
 9984.23453.33519991.134450.6631 9994.79449.82759998.512449.393410002.23449.2486
10013.41 449.25210017.14 449.03910020.86448.510510024.59448.856910028.32452.2957
10032.05455.378310035.77458.134410043.23463.037710046.96466.110610058.14477.6434
10069.32488.447710073.05491.500510076.78 493.76410087.96501.765710098.48508.7228
#Mann= 3 , 0 , 0
9896.146    0.12       09896.146    0.12       010098.48    0.12       0
#XS Ineff= 2 , 0
       0                               0
Bank Sta=9896.146,10098.48
Exp/Cntr=0.3,0.1

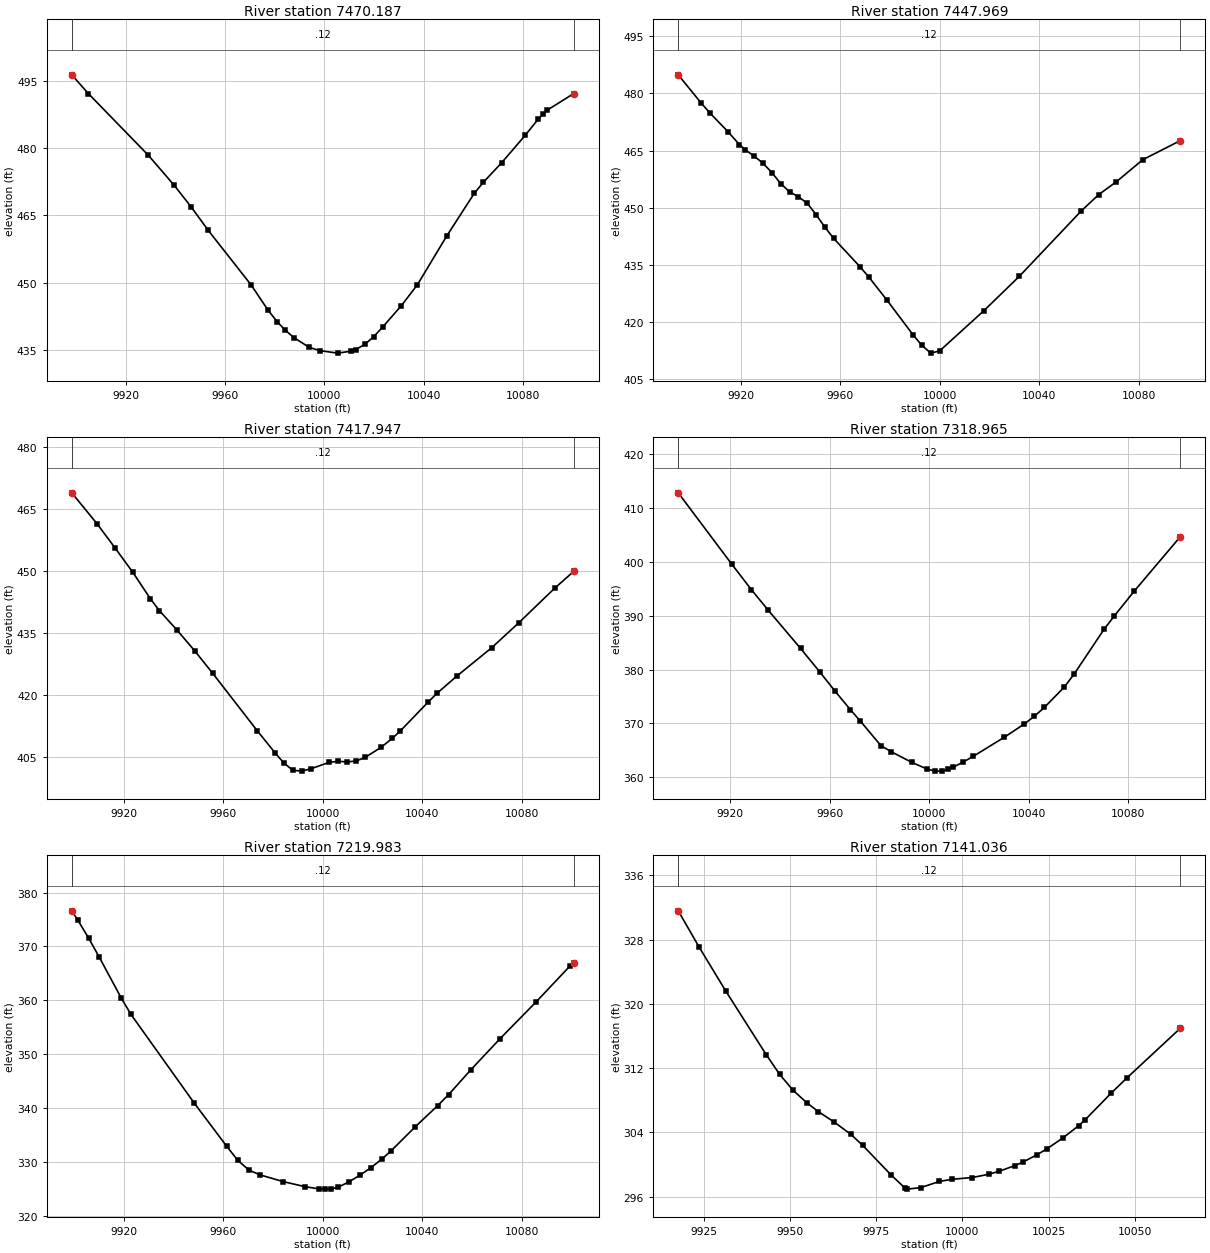
Type RM Length L Ch R = 1 ,7470.187,22.218100,22.218100,22.218100
XS GIS Cut Line= 4
1247734.85527823843154.5959158091247825.93070262843124.771708005
1247841.29528595843118.0008746721247921.40007098843077.232015659
#Sta/Elev= 30
9898.086496.27439904.793492.09099928.959 478.3729939.316471.73479946.221466.8885
9953.125461.65029970.386449.53159977.291443.85619980.957441.30399984.195439.4347
9987.648437.7895 9993.92435.58879998.162434.881510005.33434.325310010.71434.7595
10012.55 435.09310016.23436.256410019.91437.999310023.59440.203510030.96444.8447
10037.52449.578610049.36 460.43410060.41 469.87810064.09472.352910071.45476.6874
10080.92482.770310086.18486.385410088.15487.515810089.86488.419810100.59492.1162
#Mann= 3 , 0 , 0
9898.086    0.12       09898.086    0.12       010100.59    0.12       0
#XS Ineff= 2 , 0
       0                               0
Bank Sta=9898.086,10100.59
Exp/Cntr=0.3,0.1

Type RM Length L Ch R = 1 ,7447.969,30.022100,30.022100,30.022100
XS GIS Cut Line= 4
1247739.19555601843184.109804698 1247831.6400641843146.026663828
1247833.44578511843145.1667966121247925.74034876843106.745904548
#Sta/Elev= 30
9894.856484.87949904.153477.41299907.701474.78529914.798469.98489919.462466.5668
9921.894465.14589925.442463.51759928.991461.61239932.539459.20369936.087456.2901
9939.636454.15479943.184452.84459946.732451.16149950.281448.17739953.915444.7931
9957.377441.91669968.022434.43529971.571431.71399978.667425.82489989.312 416.581
9992.861413.82379996.447411.780710000.01412.367210017.78422.918110031.99431.9139
10056.87  449.0610063.98453.416510071.08 456.79310081.75462.597710096.81467.5966
#Mann= 3 , 0 , 0
9894.856    0.12       09894.856    0.12       010096.81    0.12       0
#XS Ineff= 2 , 0
       0                               0
Bank Sta=9894.856,10096.81
Exp/Cntr=0.3,0.1

Type RM Length L Ch R = 1 ,7417.947,98.981800,98.981800,98.981800
XS GIS Cut Line= 5
1247754.92008051843212.5486573581247841.93524735843174.409776579
1247846.40371592843172.2158779331247848.17537896 843171.28786389
1247938.35250298843128.121855273
#Sta/Elev= 30
9899.016468.98229909.143461.51839916.307455.72429923.471449.80989930.636 443.323
9934.218440.46799941.382435.70879948.546430.64399955.711  425.259973.621411.3384
9980.786 405.9849984.368 403.502 9987.95401.76589991.532401.55059995.136402.1008
10002.47403.6656 10006.1403.931810009.74403.788610013.38403.991210017.01404.8702
10023.41 407.30110027.93409.4765   10031411.174810042.48418.355110046.11420.5013
 10053.8424.522910067.94431.452310078.85437.4972 10093.4 445.94510100.98449.9722
#Mann= 3 , 0 , 0
9899.016    0.12       09899.016    0.12       010100.98    0.12       0
#XS Ineff= 2 , 0
       0                               0
Bank Sta=9899.016,10100.98
Exp/Cntr=0.3,0.1

Type RM Length L Ch R = 1 ,7318.965,98.981800,98.981800,98.981800
XS GIS Cut Line= 6
1247808.60003617843316.197571658 1247861.1046024843281.074137516
1247890.45655455843258.8486208911247892.00878251843257.587435593
1247916.09511945843238.9664000821247972.94160305 843198.89623703
#Sta/Elev= 29
9899.013412.72219920.587399.48619928.481394.75959935.108391.04179948.218383.9073
9956.112379.45919962.183375.94179968.199 372.5929972.315370.42169980.545 365.906
9984.661364.78219992.891362.8176    9999 361.58710002.36 361.17910005.32361.1971
10007.72 361.54910009.47361.871310013.62362.849210017.76363.9353 10030.2367.4545
10038.27369.925910042.29371.3473 10046.3372.971410054.33376.756810058.34379.1991
10070.38387.4956 10074.4389.901210082.43394.502510100.99404.5929
#Mann= 3 , 0 , 0
9899.013    0.12       09899.013    0.12       010100.99    0.12       0
#XS Ineff= 2 , 0
       0                               0
Bank Sta=9899.013,10100.99
Exp/Cntr=0.3,0.1

Type RM Length L Ch R = 1 ,7219.983,78.947500,78.947500,78.947500
XS GIS Cut Line= 5
1247880.35980467843397.331073899 1247923.1675442 843362.13501938
1247955.79988246 843331.792558571247957.31839563843330.490975778
1248030.95599172843262.857469428
#Sta/Elev= 30
9899.022376.60399901.541374.81069905.788 371.5569910.035368.04199918.893360.4477
9922.777357.41859948.262340.93769961.363332.89389965.843330.28189970.323328.4819
9974.803327.59549983.922326.37229992.723325.42219998.376325.0043   10001 324.958
 10003.3324.970710006.06325.297910010.52326.306310014.97327.551310019.42328.9586
10023.88330.581810027.55332.103510037.24336.546410046.15340.429910050.61342.4978
10059.52347.0923 10071.2352.831810085.75359.677510099.61366.454310100.98367.0052
#Mann= 3 , 0 , 0
9899.022    0.12       09899.022    0.12       010100.98    0.12       0
#XS Ineff= 2 , 0
       0                               0
Bank Sta=9899.022,10100.98
Exp/Cntr=0.3,0.1

Type RM Length L Ch R = 1 ,7141.036,65.148800,65.148800,65.148800
XS GIS Cut Line= 6
1247946.17391451843435.4546266971247980.32058996843413.382559036
1248000.86791946843397.7253402231248025.06056925843374.582046122
1248026.47478277843373.1678325171248057.15249724843341.956258331
#Sta/Elev= 30
9917.522331.5797 9923.51327.11669931.323321.58679943.043313.6821 9946.95311.2191
9950.856309.23119954.763 307.7069958.181306.57979962.821 305.2659967.595303.7583
9971.071302.3739 9979.32298.68059983.445 297.0179984.014296.92469987.928297.1119
9993.349297.88739997.009298.147210002.84298.369510007.59298.767210010.63299.1401
10015.17299.845310017.49300.273510021.71301.215210024.44301.916310029.12303.2799
 10033.8304.839910035.51305.505110043.16308.866610047.84310.805310063.26316.9555
#Mann= 3 , 0 , 0
9917.522    0.12       09917.522    0.12       010063.26    0.12       0
#XS Ineff= 2 , 0
       0                               0
Bank Sta=9917.522,10063.26
Exp/Cntr=0.3,0.1

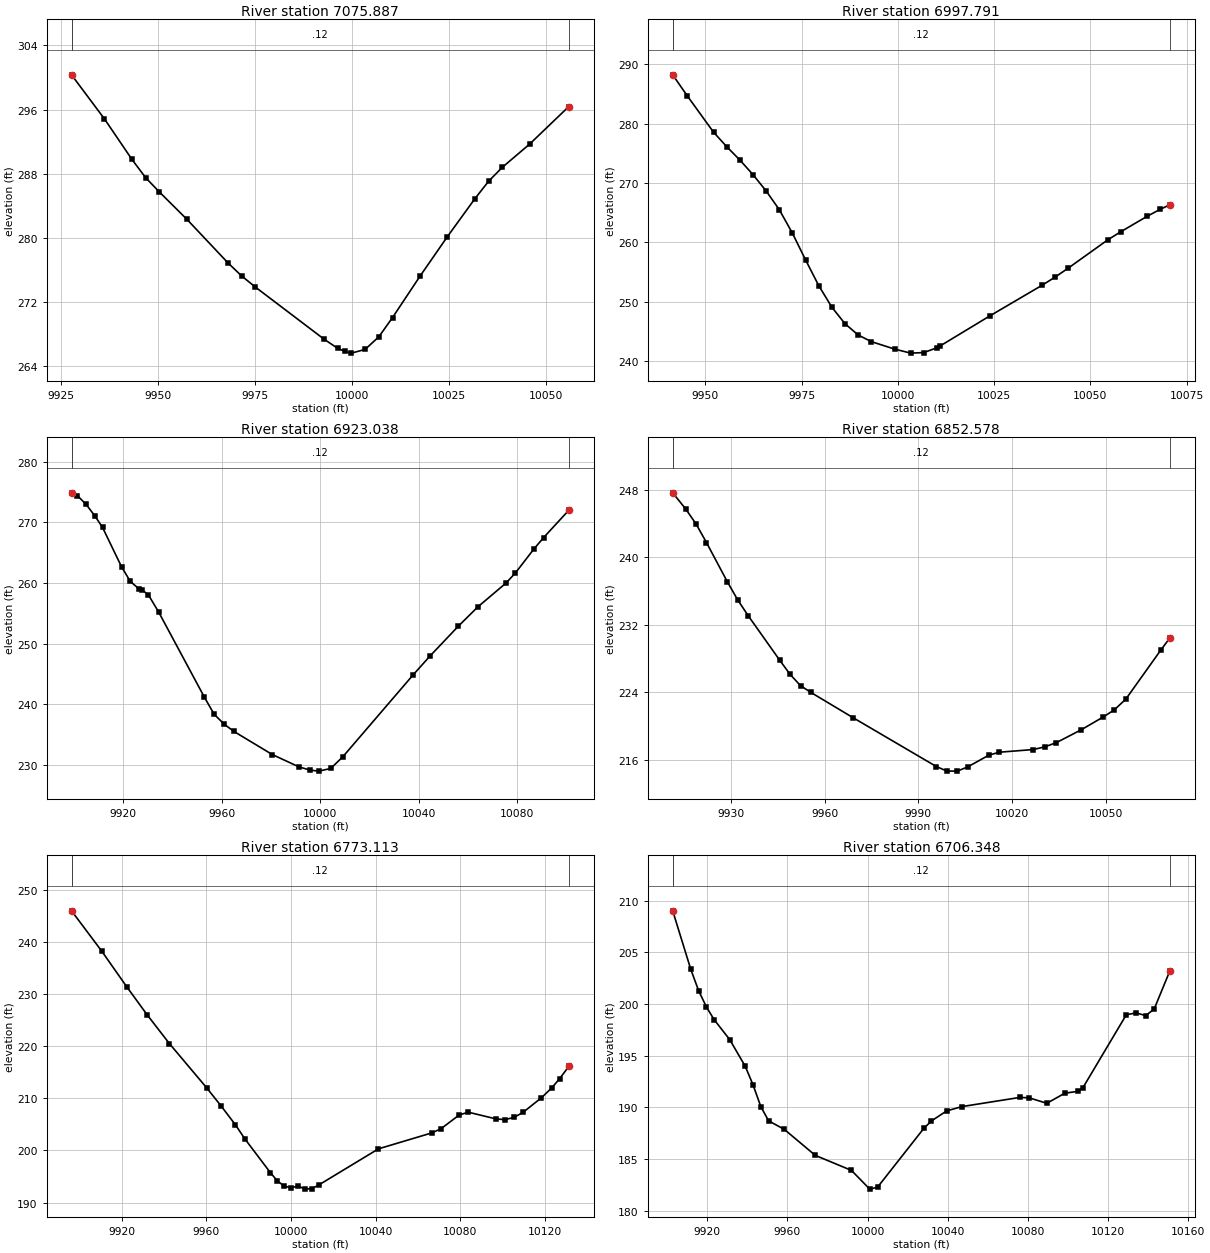
Type RM Length L Ch R = 1 ,7075.887,78.096000,78.096000,78.096000
XS GIS Cut Line= 2
1247989.26114243843460.1594394871248108.18475354843412.416383931
#Sta/Elev= 23
9927.807300.33649936.291294.84029943.362289.80139946.897287.51889950.432285.7377
9957.503282.34029968.109 276.8969971.644275.2636 9975.18273.87569992.857267.3888
9996.392266.23589998.228265.85579999.927265.638410003.46266.0997   10007267.6713
10010.53270.0699 10017.6275.220110024.67280.157710031.75284.884610035.28287.0608
10038.82288.800510045.89291.710110055.96296.3819
#Mann= 3 , 0 , 0
9927.807    0.12       09927.807    0.12       010055.96    0.12       0
#XS Ineff= 2 , 0
       0                               0
Bank Sta=9927.807,10055.96
Exp/Cntr=0.3,0.1

Type RM Length L Ch R = 1 ,6997.791,74.753100,74.753100,74.753100
XS GIS Cut Line= 2
1248006.62225354843525.2636061541248130.75419799843489.673328376
#Sta/Elev= 29
9941.542288.19189945.324284.6564 9952.15278.54579955.563276.11859958.976273.8703
9962.389271.41239965.802 268.6739969.215265.52339972.628 261.5699976.041257.0818
9979.454252.76639982.867249.1221 9986.28246.34459989.693244.45269993.106243.3343
9999.164242.074610003.35241.395610006.76241.488410010.17242.301310011.07242.6304
10023.82247.623510037.48252.812410040.89254.1951 10044.3255.705410054.54260.4478
10057.95261.821610064.78264.414510068.19265.587910070.68266.3499
#Mann= 3 , 0 , 0
9941.542    0.12       09941.542    0.12       010070.68    0.12       0
#XS Ineff= 2 , 0
       0                               0
Bank Sta=9941.542,10070.68
Exp/Cntr=0.3,0.1

Type RM Length L Ch R = 1 ,6923.038,70.459700,70.459700,70.459700
XS GIS Cut Line= 6
 1248031.0521249843616.1527378481248056.86491378843604.804121745
1248080.45368672843591.2677572041248097.64944504843578.050322775
1248142.89664332843536.1881339921248196.26574659843502.468820744
#Sta/Elev= 30
9899.046274.88039901.419274.42169905.003272.95679908.586271.0321 9911.63269.1751
9919.338 262.6869922.922260.24769926.506259.01019927.801258.82069930.248258.0426
9934.393255.22669952.944241.18849956.941238.34059961.079236.67659964.985235.4996
9980.534231.69299991.425229.64329995.974229.11159999.473228.949310004.29229.3901
10009.19231.309210037.78244.847410044.52247.910310056.03252.837510064.02256.0521
10075.51260.002810079.31261.670610086.91265.670710090.71267.480410100.96272.0071
#Mann= 3 , 0 , 0
9899.046    0.12       09899.046    0.12       010100.96    0.12       0
#XS Ineff= 2 , 0
       0                               0
Bank Sta=9899.046,10100.96
Exp/Cntr=0.3,0.1

Type RM Length L Ch R = 1 ,6852.578,79.465100,79.465100,79.465100
XS GIS Cut Line= 3
1248058.70558688843639.8469394871248162.83085757843619.250732098
1248209.78486928843594.650180227
#Sta/Elev= 27
9911.383247.61649915.507245.72039918.851243.93539922.196241.72859928.884237.0743
9932.229234.91439935.573233.05119945.606227.81079948.951226.12369952.295224.7833
 9955.64223.97799969.017221.01299995.772215.20799999.117214.675210002.46 214.666
10005.81215.169110012.49216.538710015.84216.903710026.77217.221410030.47217.5406
10034.18218.041410042.18219.571110049.25221.0933 10052.7221.9161 10056.4 223.188
10067.51 228.95210070.53 230.455
#Mann= 3 , 0 , 0
9911.383    0.12       09911.383    0.12       010070.53    0.12       0
#XS Ineff= 2 , 0
       0                10014.51       0
Bank Sta=9911.383,10070.53
Exp/Cntr=0.3,0.1

Type RM Length L Ch R = 1 ,6773.113,66.765000,66.765000,66.765000
XS GIS Cut Line= 6
1248030.05975354843669.3608283761248088.21947577843693.666383932
1248106.44864243843698.8747172651248146.37919799843698.874717265
1248170.68475354843688.4580505981248236.65697577843632.034439487
#Sta/Elev= 30
9896.187245.9989 9910.42238.29239922.348231.3952 9931.93226.05289942.484220.5169
9960.049212.05449966.874208.57639973.698204.93259978.198202.21559990.275195.7252
9993.556194.16439996.837193.134910000.12192.8798 10003.4193.156910006.68192.5848
10009.96192.691710013.24 193.41110041.37 200.318 10066.6203.377610070.91204.1638
10079.55206.818610083.87207.348810096.82206.075410101.13205.918310105.45206.3479
10109.77207.3225 10118.4210.112710123.23211.974310127.04213.784610131.38216.1306
#Mann= 3 , 0 , 0
9896.187    0.12       09896.187    0.12       010131.38    0.12       0
#XS Ineff= 2 , 0
       0                               0
Bank Sta=9896.187,10131.38
Exp/Cntr=0.3,0.1

Type RM Length L Ch R = 1 ,6706.348,80.255600,80.255600,80.255600
XS GIS Cut Line= 4
1248051.82928815843812.9836164411248149.85142025843750.958050609
1248185.44169804 843730.124717281248252.28197581843668.492772833
#Sta/Elev= 30
9902.738209.00949911.781203.33679915.663201.29069919.546199.71579923.428198.4776
9931.193196.55369938.958193.96359942.841192.16759946.723190.06489950.605188.6913
 9958.37 187.876  9973.9185.35199991.938183.900410001.08182.087810004.96182.2736
10028.06187.965610031.86188.684210039.46189.654210047.06190.071510076.06190.9614
 10080.7 190.91610089.45190.390310098.37191.3644 10104.9191.5465 10107.3191.8499
 10129.1198.953310133.94199.135410138.78198.8763   10143199.504510150.89203.2258
#Mann= 3 , 0 , 0
9902.738    0.12       09902.738    0.12       010150.89    0.12       0
#XS Ineff= 2 , 0
       09988.989                       0
Bank Sta=9902.738,10150.89
Exp/Cntr=0.3,0.1

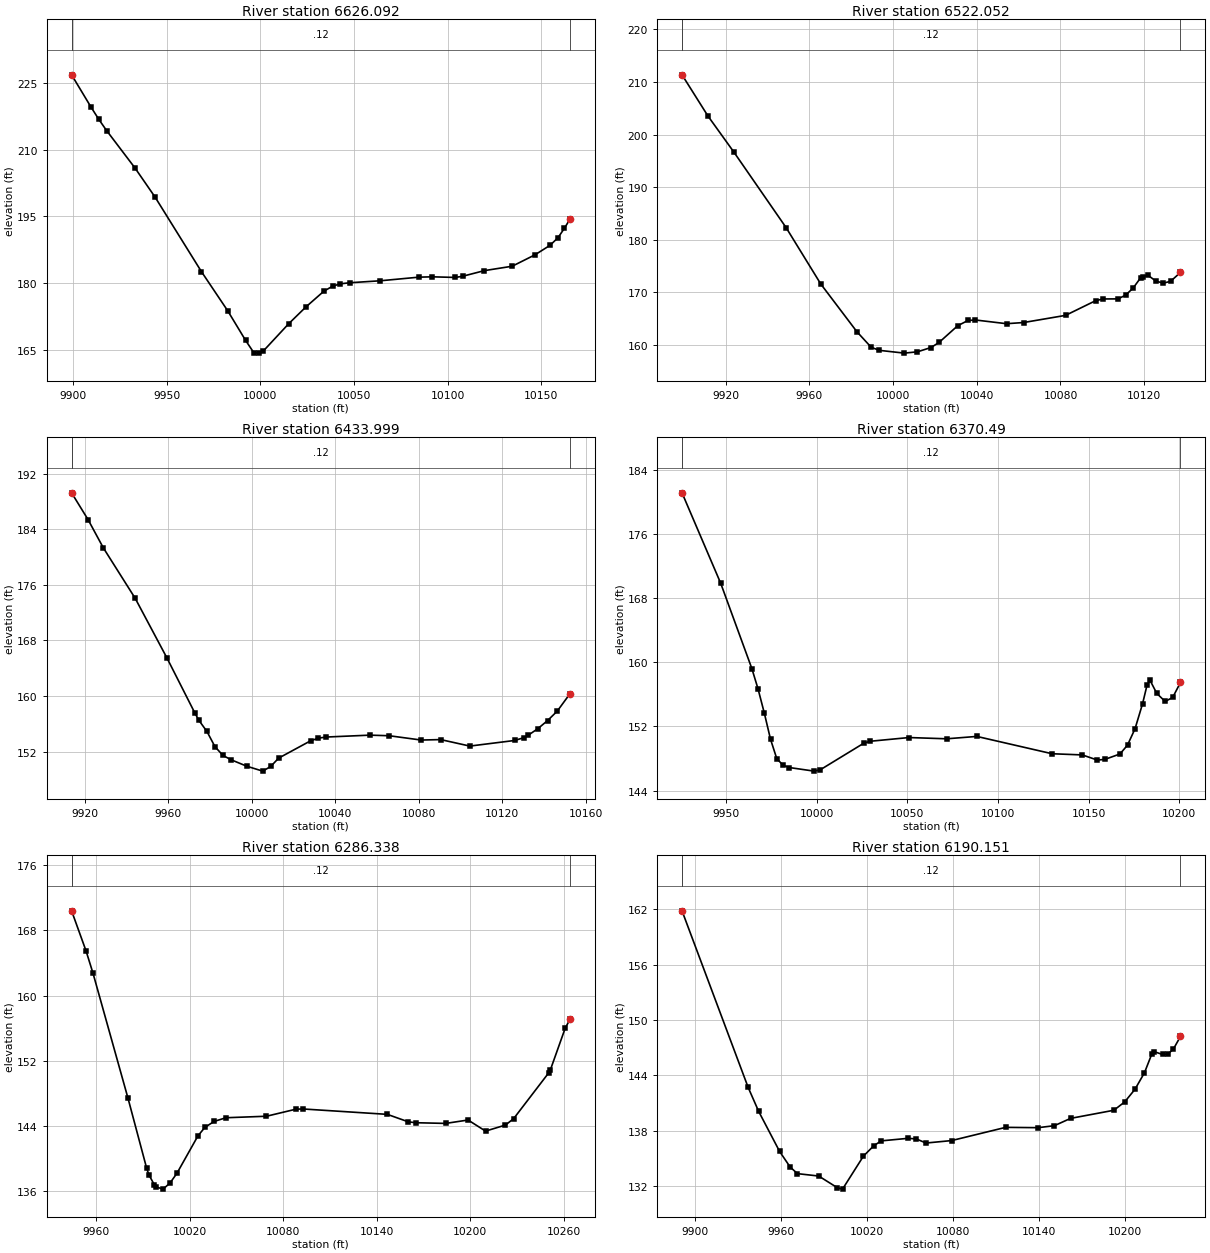
Type RM Length L Ch R = 1 ,6626.092,104.040600,104.040600,104.040600
XS GIS Cut Line= 6
1248093.91683331843894.3787491721248138.37920004843859.818196253
1248170.78931031843827.6905924311248202.59232993843796.478666888
1248227.10836465843763.9788839321248269.64308688843697.138606154
#Sta/Elev= 30
 9899.05226.73239909.441219.49549913.597216.75559917.752214.25019932.981205.8358
9943.673199.33959968.476182.6242 9982.46173.89459992.077167.22329996.444 164.484
    9999164.378910001.32164.754210015.11170.969110024.31174.728210033.88178.2467
10038.57179.379410042.69179.901510047.61180.145610063.95180.585110084.63181.3963
10091.79181.478310104.16181.335410108.05181.599110119.72182.864110134.57183.8488
10146.79186.414110154.72188.513610159.01190.213910162.49192.3595 10165.5194.4329
#Mann= 3 , 0 , 0
 9899.05    0.12       0 9899.05    0.12       0 10165.5    0.12       0
#XS Ineff= 2 , 0
       0                               0
Bank Sta=9899.05,10165.5
Exp/Cntr=0.3,0.1

Type RM Length L Ch R = 1 ,6522.052,88.052700,88.052700,88.052700
XS GIS Cut Line= 6
1248161.18947458843960.3201437081248223.89608725843911.949605697
 1248241.4768589843900.8657328171248243.22517342843899.894446902
1248267.03892021843880.2983283761248309.57364243843783.944161709
#Sta/Elev= 30
9899.191211.33249911.605 203.4959924.035196.62149948.896182.3333 9965.47171.6197
9982.708162.56869989.567159.59719993.445 159.01710005.38158.487510011.64158.7363
10018.13159.551910021.97160.511610030.87163.680510035.79164.689710039.38164.7798
10054.21164.076510062.34164.295610082.42165.656710096.76168.441910100.35 168.773
10107.52168.788410111.11169.502610114.69170.836510118.28172.7873 10119.2173.0335
10121.86173.251810125.45172.204210129.04171.764910132.62172.129810137.33173.8179
#Mann= 3 , 0 , 0
9899.191    0.12       09899.191    0.12       010137.33    0.12       0
#XS Ineff= 2 , 0
       0                10031.11       0
Bank Sta=9899.191,10137.33
Exp/Cntr=0.3,0.1

Type RM Length L Ch R = 1 ,6433.999,63.508800,63.508800,63.508800
XS GIS Cut Line= 3
1248226.82928821 844008.816949771248336.20428815843943.712783098
1248414.85012153843864.546116441
#Sta/Elev= 30
9913.624189.2421  9921.5185.39399928.854181.30899944.126174.04489959.399165.4252
9972.815157.47579974.671156.47129978.489154.88579982.307152.71029986.125151.4467
9989.943 150.8289997.579 149.88410005.22149.177110009.03149.843610012.85151.0495
10028.12153.535510031.94153.931410035.76154.086310056.56154.356510065.81 154.273
10081.18153.650810090.49153.718210104.46152.783410125.93153.590410130.55154.0093
10132.39 154.33210137.04155.2846 10141.7156.449210146.36157.8156 10152.5160.3347
#Mann= 3 , 0 , 0
9913.624    0.12       09913.624    0.12       0 10152.5    0.12       0
#XS Ineff= 2 , 0
       0                10037.87       0
Bank Sta=9913.624,10152.5
Exp/Cntr=0.3,0.1

Type RM Length L Ch R = 1 , 6370.49,84.152500,84.152500,84.152500
XS GIS Cut Line= 3
1248252.35012153844042.6711164411248364.32928815844007.775283098
1248461.20428815843883.296116441
#Sta/Elev= 30
9925.664181.12099947.004169.84329964.187159.21269967.623  156.66 9971.06153.6613
9974.496150.38979977.932 147.9819981.369147.15989984.805146.86819998.551146.4182
10001.99146.592410026.04149.911210029.48150.1423 10050.9150.606110071.68150.4502
10088.31150.745810129.88 148.58510146.51148.439510154.83147.797710158.99147.8842
 10167.3148.556110171.46149.663410175.62151.709310179.77154.827610182.26157.1706
10183.93 157.72210187.61156.108310192.24155.1043 10196.4155.611410200.69157.4787
#Mann= 3 , 0 , 0
9925.664    0.12       09925.664    0.12       010200.69    0.12       0
#XS Ineff= 2 , 0
       0                10039.26       0
Bank Sta=9925.664,10200.69
Exp/Cntr=0.3,0.1

Type RM Length L Ch R = 1 ,6286.338,96.186600,96.186600,96.186600
XS GIS Cut Line= 3
1248305.47512153844139.5461164271248370.05845484844070.275283098
1248524.22512153843906.212783098
#Sta/Elev= 30
9944.232170.40839953.536165.47249958.022162.7183 9980.45147.39029992.428138.7923
9993.906137.98339997.239136.81079998.392 136.53210002.88136.251210007.36136.9927
10011.85138.204410025.31142.788610029.79143.836410035.73144.562910043.26145.0131
10069.28145.196910088.28146.067410092.79146.088510146.81145.428110160.31144.5083
 10165.1144.401110184.26144.317410198.64144.733210209.84143.372810222.59144.1124
10227.85144.896310250.36150.520110251.34150.832410260.92155.987810264.07157.1145
#Mann= 3 , 0 , 0
9944.232    0.12       09944.232    0.12       010264.07    0.12       0
#XS Ineff= 2 , 0
       0                10054.72       0
Bank Sta=9944.232,10264.07
Exp/Cntr=0.3,0.1

Type RM Length L Ch R = 1 ,6190.151,78.692400,78.692400,78.692400
XS GIS Cut Line= 3
1248333.01114243844181.5136061541248457.00709151844120.344624672
1248560.74696419843938.118062171
#Sta/Elev= 30
9890.672 161.8459936.857142.67879944.174140.08459958.807135.73589966.124134.0538
9971.252133.33199986.084133.07269999.049131.809610002.71131.652110017.34135.2419
10024.66136.376710029.77136.888510048.65 137.16610054.34137.088910060.97136.6535
10078.85136.9189 10116.6138.353810139.25138.319410150.58138.5338 10161.9139.3273
10192.11140.208810199.66141.111110206.86142.487110213.49 144.28410218.53146.2851
10220.12146.575310226.08146.259710229.86146.313210233.63146.836210238.62148.2233
#Mann= 3 , 0 , 0
9890.672    0.12       09890.672    0.12       010238.62    0.12       0
#XS Ineff= 2 , 0
       0                10034.37       0
Bank Sta=9890.672,10238.62
Exp/Cntr=0.3,0.1

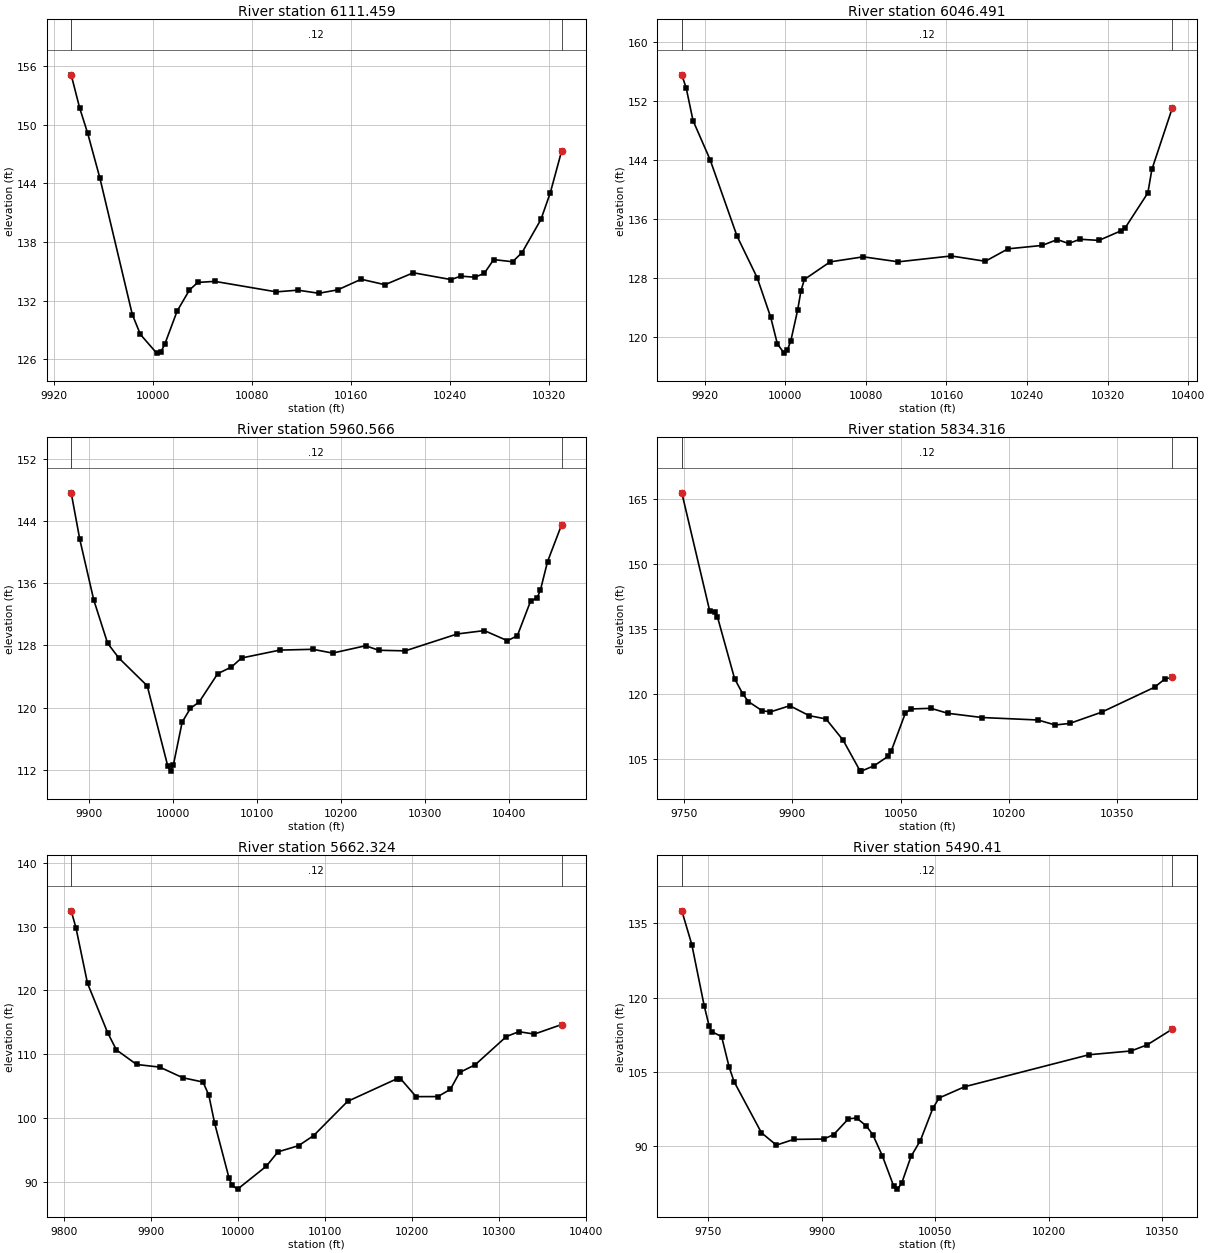
Type RM Length L Ch R = 1 ,6111.459,64.967800,64.967800,64.967800
XS GIS Cut Line= 6
1248357.80407926844209.0244247491248376.99024383844209.166094744
1248424.77936279844209.7935437221248450.88946257844206.277335494
1248469.12170198844201.9432554141248615.00043641843957.649312171
#Sta/Elev= 30
9933.657155.10729940.441151.74479947.003149.12319956.846144.55019983.095 130.567
9989.657128.5289 10002.8126.617910006.11 126.71910009.42127.554710019.35 130.923
10029.33133.082210036.07133.8576 10049.9 133.96210099.58132.8894   10117133.0626
10133.97132.745810149.25133.096810168.19134.179110187.46 133.62210210.39134.8452
10240.96134.1445 10248.6134.500210260.07134.388610267.71134.778210275.35 136.192
10290.64135.972810298.28136.905910313.57140.297710321.21143.058710330.26147.2812
#Mann= 3 , 0 , 0
9933.657    0.12       09933.657    0.12       010330.26    0.12       0
#XS Ineff= 2 , 0
       0                10039.58       0
Bank Sta=9933.657,10330.26
Exp/Cntr=0.3,0.1

Type RM Length L Ch R = 1 ,6046.491,85.924800,85.924800,85.924800
XS GIS Cut Line= 6
1248340.63038998844292.0551548981248377.36738072844283.006743677
1248438.51429368844271.8613876811248440.48085768844271.497209103
1248468.24002278844265.5956916671248642.12717253843954.394103838
#Sta/Elev= 30
9897.224155.56339901.624153.74899908.382149.34999925.276144.06439952.083 133.676
9972.092 128.0349985.432122.70539992.101119.06769998.772117.813510002.12118.2592
10005.48119.501610012.19123.623910015.54 126.26510018.89 127.80410044.48130.1913
10077.41130.877110112.13130.198710164.75130.992910198.57130.273810221.12131.9609
10254.95132.420810269.98 133.21610281.25132.684310292.53  133.2610311.32133.1049
   10333134.388310337.63134.851710359.91139.538410363.93142.729710384.08151.0196
#Mann= 3 , 0 , 0
9897.224    0.12       09897.224    0.12       010384.08    0.12       0
#XS Ineff= 2 , 0
       0                 10024.1       0
Bank Sta=9897.224,10384.08
Exp/Cntr=0.3,0.1

Type RM Length L Ch R = 1 ,5960.566,126.250500,126.250500,126.250500
XS GIS Cut Line= 6
1248324.99609614844382.9965343951248404.42317947844369.107645506
1248453.90234614844352.1805621731248460.84679058844343.934034395
1248482.11415169844303.1354232841248698.55078364843973.925353838
#Sta/Elev= 30
9878.731147.59669888.948141.63579905.601133.84359922.121128.28259935.576126.3812
9969.274122.81869993.546112.58619997.014111.873710000.48112.717310010.88118.1761
10020.71119.940510031.01120.739310053.16124.385110069.55125.238310081.49126.3941
10127.13 127.40810166.39127.510910189.95127.027610229.22127.966210244.92127.3863
10276.33127.3118 10338.3129.481310370.56129.912210398.02128.615110409.83129.2527
10425.53133.675710433.39134.116910437.31 135.11810445.79138.770210462.47143.4819
#Mann= 3 , 0 , 0
9878.731    0.12       09878.731    0.12       010462.47    0.12       0
#XS Ineff= 2 , 0
       0                10035.79       0
Bank Sta=9878.731,10462.47
Exp/Cntr=0.3,0.1

Type RM Length L Ch R = 1 ,5834.316,171.991900,171.991900,171.991900
XS GIS Cut Line= 4
1248328.03429058844541.9411235161248480.85961678844450.425973435
1248795.49525945844243.5904281361248896.03342253844169.237853838
#Sta/Elev= 30
9746.831166.41979785.614139.13489793.262138.8999 9796.16137.88779820.031123.5913
9831.503120.04829839.151 118.3229858.271116.20839869.744115.95699896.512117.3731
9923.281115.09139946.794 114.3199970.351109.45359993.909102.37149995.622102.3058
10013.54103.556610033.17105.7707 10037.1106.929410056.73115.677810064.58116.6268
10092.07116.776810115.62115.628610162.74114.6594 10240.5114.085110264.39112.9397
10284.45113.293810328.67115.879510402.12 121.63210416.19123.500910426.54123.9508
#Mann= 3 , 0 , 0
9746.831    0.12       09746.831    0.12       010426.54    0.12       0
#XS Ineff= 2 , 0
       0                               0
Bank Sta=9746.831,10426.54
Exp/Cntr=0.3,0.1

Type RM Length L Ch R = 1 ,5662.324,171.914000,171.914000,171.914000
XS GIS Cut Line= 6
 1248401.8190128844585.3439012931248622.38860044844553.664242649
1248648.27345101844548.8119303741248670.57272151 844542.09965646
1248700.53348319844530.2186798471248937.84331836844426.923762404
#Sta/Elev= 30
9808.455132.47759813.938129.81919827.215121.1209 9850.45113.35799860.408110.6997
9883.642108.41069910.196107.9985 9936.75106.33229959.985105.65689966.623103.6003
9973.26299.23635 9989.82  90.6469993.12689.457599999.732 88.886210032.7592.48214
 10046.194.7242710069.7895.6924110087.0997.2722510126.08102.630410183.34106.2068
10186.91106.1903 10204.8103.373310229.85103.383510244.16104.5037 10254.9107.1575
10272.79108.368110308.57112.785510322.88113.546810340.77113.171310372.01114.6607
#Mann= 3 , 0 , 0
9808.455    0.12       09808.455    0.12       010372.01    0.12       0
#XS Ineff= 2 , 0
       0                               0
Bank Sta=9808.455,10372.01
Exp/Cntr=0.3,0.1

Type RM Length L Ch R = 1 , 5490.41,171.914100,171.914100,171.914100
XS GIS Cut Line= 6
1248417.00998503844719.8925124041248643.78949891844730.743206849
1248687.27992313844694.4720014441248751.68538033844645.403918313
1248830.42144336844571.2379985151248954.11936003844447.540081849
#Sta/Elev= 30
9715.331137.4807 9728.54130.68469744.963118.29789751.532114.21479754.817 113.145
9767.955112.11989777.809106.01889784.378103.04339820.50992.754899840.21690.25655
9863.20891.413599902.62391.480259915.76292.354219935.46995.566759946.21195.72203
9959.02794.125639967.57192.385989980.38888.047029994.98482.0920210000.2381.38799
10005.6782.5384810018.1187.9810710030.4991.18579   1004797.7052310055.2699.76483
10089.04 102.03110253.16108.472410308.83109.235710330.36110.491310363.07113.6206
#Mann= 3 , 0 , 0
9715.331    0.12       09715.331    0.12       010363.07    0.12       0
#XS Ineff= 2 , 0
       09951.191                       0
Bank Sta=9715.331,10363.07
Exp/Cntr=0.3,0.1