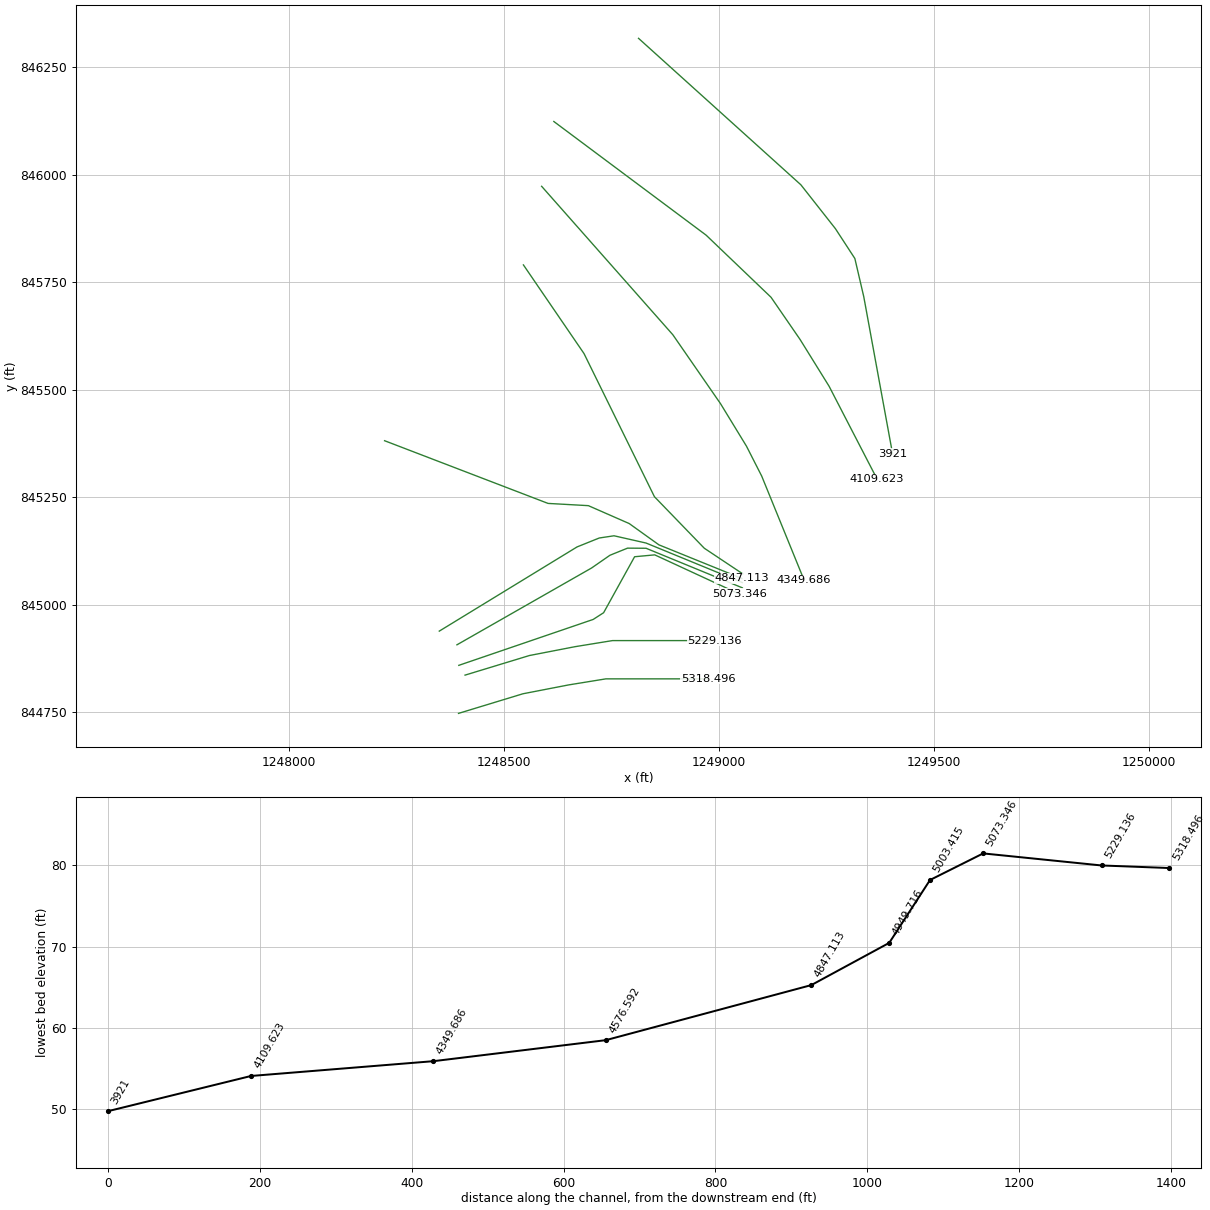
HEC-RAS study 123_ras.prj: 123

--- 123_ras.g01 (geometry) --- (continued)

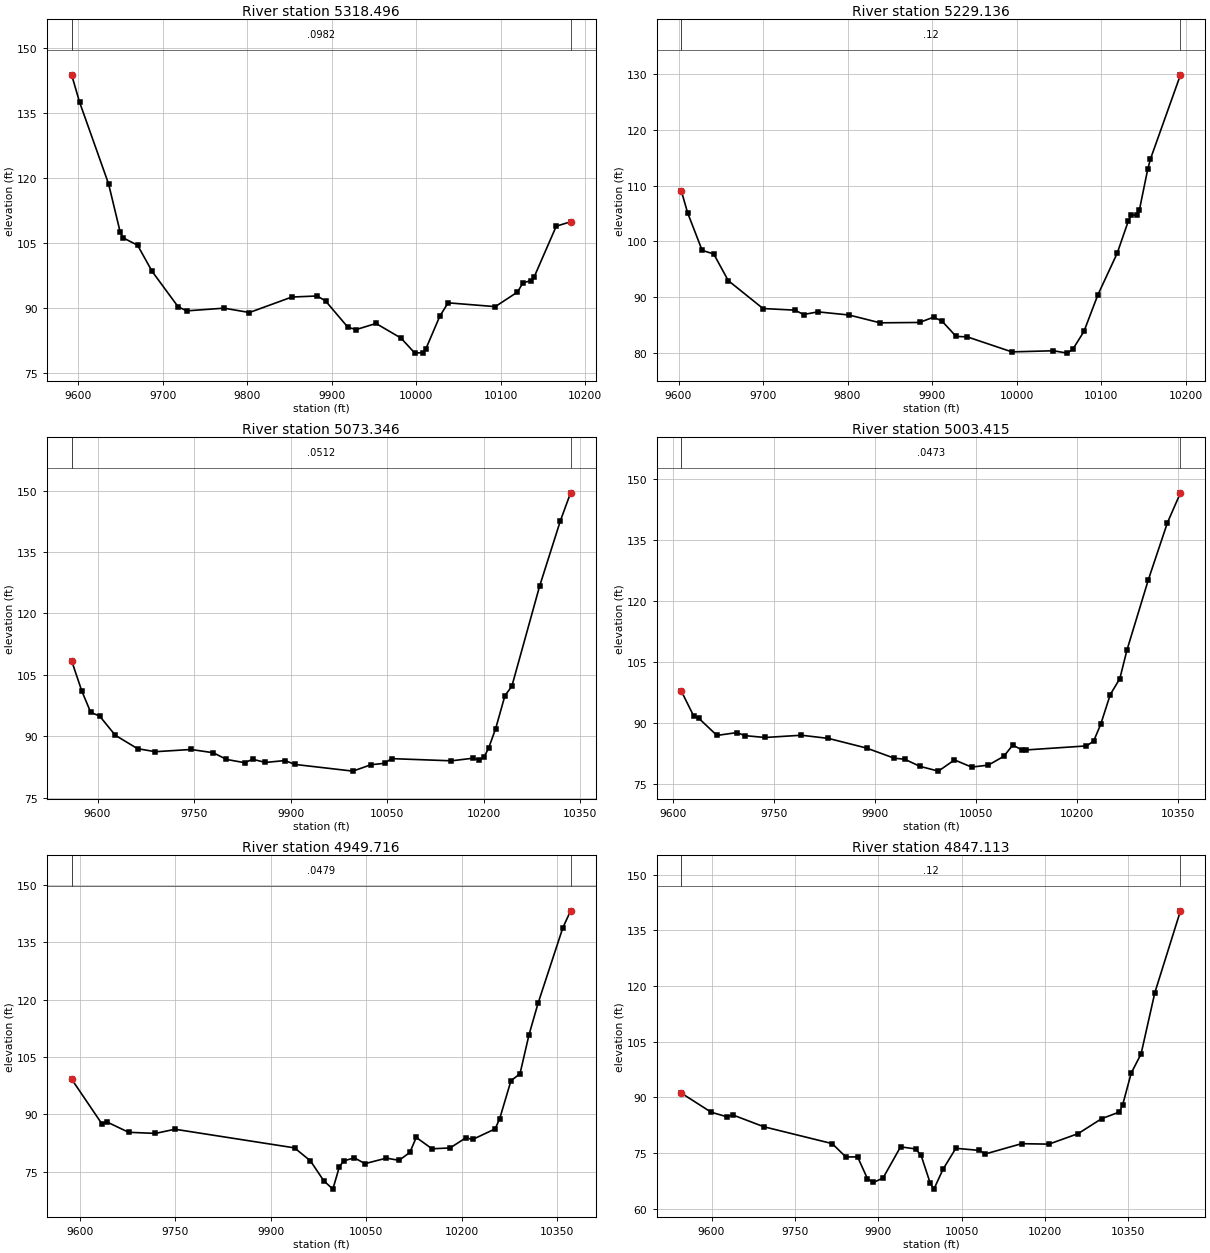
Type RM Length L Ch R = 1 ,5318.496,89.359600,89.359600,89.359600
XS GIS Cut Line= 6
1248394.90350355844747.6739070791248544.64308688844793.246823746
1248650.97989243 844813.863143191248737.78544799844827.969045968
1248885.35489243844827.9690459681248975.41565632844827.969045968
#Sta/Elev= 30
 9592.36143.92049601.824137.57959636.119118.72929649.836107.59939653.266106.2835
9670.413104.5793 9687.5698.547849718.42590.349919728.71389.423169772.67290.04652
 9802.75 89.03919852.87992.611379882.81792.860289892.78891.722759919.379 85.6013
9929.35185.118269952.52186.513889982.04983.141419998.45379.66361 10008.379.79141
10011.5880.6792310027.9888.1824610037.8291.27758 10093.690.3985510119.8493.75224
10126.4195.8935610136.2596.4135810139.5397.1994310165.78108.970810182.77 109.993
#Mann= 3 , 0 , 0
 9592.36  0.0982       0 9592.36  0.0982       010182.77  0.0982       0
#XS Ineff= 2 , 0
       09889.889        10034.69       0
Bank Sta=9592.36,10182.77
Exp/Cntr=0.3,0.1

Type RM Length L Ch R = 1 ,5229.136,155.790100,155.790100,155.790100
XS GIS Cut Line= 6
1248410.09447577844836.649601524 1248559.8340591844882.222518191
1248666.17086466844902.8388376351248752.97642021844916.944740413
1248900.54586466844916.9447404131248990.60662855844916.944740413
#Sta/Elev= 30
9603.495108.96859610.798105.12649627.94698.409969641.66397.75928 9658.8192.98931
9699.96387.976569737.68787.688989747.97586.902639764.99287.378479801.75386.81555
9838.51485.41261 9885.2185.478349901.82986.432349911.801 85.7155 9928.4282.97655
9941.71582.892599994.397  80.20510043.6180.4035910060.0179.9806510066.5880.68475
 10079.783.86501 10096.190.3992210119.0797.9022610132.19103.656710135.47104.6714
10142.03104.781710145.32105.657110155.16112.933110158.44114.796410193.91129.8757
#Mann= 3 , 0 , 0
9603.495    0.12       09603.495    0.12       010193.91    0.12       0
#XS Ineff= 2 , 0
       09901.803        10063.12       0
Bank Sta=9603.495,10193.91
Exp/Cntr=0.3,0.1

Type RM Length L Ch R = 1 ,5073.346,69.931100,69.931100,69.931100
XS GIS Cut Line= 6
1248395.55454521844859.3781894871248708.05454521 844966.14902282
1248732.36010077 844981.774022821248804.40871188845111.982356154
1248851.28371188845116.3226339311249048.33232299845025.176800598
#Sta/Elev= 30
9559.721108.42049575.521101.05089589.37795.819189603.23294.922589627.47990.24309
9662.11886.949249689.82986.209759745.25186.755069779.88985.952099800.294 84.3239
9828.38383.527459841.20684.357259860.80483.58417 9891.1884.047399906.78183.10025
9996.70481.4647510024.9283.0317910046.1383.3765610056.7484.52189 10149.983.98128
10182.6784.6083810193.44 84.252910200.6284.8996610207.8187.1627610218.59 91.8583
10232.9699.9025710243.74102.209110286.86126.654610319.19142.649810335.02149.4493
#Mann= 3 , 0 , 0
9559.721  0.0512       09559.721  0.0512       010335.02  0.0512       0
#XS Ineff= 2 , 0
       09861.916        10066.65       0
Bank Sta=9559.721,10335.02
Exp/Cntr=0.3,0.1

Type RM Length L Ch R = 1 ,5003.415,53.698500,53.698500,53.698500
XS GIS Cut Line= 6
1248391.21426743844907.1212450421248704.58232299845085.940689487
1248747.11704521845115.4545783761248787.91565632845131.947633931
1248831.05801743845131.6872172651249055.01635077845039.673328376
#Sta/Elev= 30
9611.93597.821989630.38591.67117 9637.9491.162019664.68286.980699694.60187.68258
9705.93386.935869736.15286.474319790.45687.027559830.58886.248239887.24983.87381
9928.801 81.3595 9943.9181.132849966.57579.377349994.176 78.192410018.1480.95263
10043.6379.1873510068.5179.6696510091.5381.84251 10104.984.6177510118.6983.38318
10125.0183.4119710214.4684.39896 10225.185.5521210235.7489.7400610249.9397.04221
10264.12100.952410274.76108.008310306.68125.362310335.05139.386410354.36146.7046
#Mann= 3 , 0 , 0
9611.935  0.0473       09611.935  0.0473       010354.36  0.0473       0
#XS Ineff= 2 , 0
       0 9901.89        10063.35       0
Bank Sta=9611.935,10354.36
Exp/Cntr=0.3,0.1

Type RM Length L Ch R = 1 ,4949.716,102.603600,102.603600,102.603600
XS GIS Cut Line= 6
1248350.15523966844938.9788839311248670.46875084845134.736331239
1248722.23411986845155.5679002811248756.57531351845160.708867628
1248831.05801743845143.8399950421249055.01635077845051.826106154
#Sta/Elev= 30
9586.71599.238029634.22987.554429641.89388.053469676.38285.321889718.534 85.0321
9749.19186.122619937.189 81.24559962.18277.854659983.24272.630559997.50470.45144
10007.8176.3276910014.6877.8526710031.3878.6357210047.9777.1162810081.5478.55637
10101.7277.9879110118.5480.0544610128.6383.9770510153.4381.00847 10181.881.22514
10206.6383.8804710217.2783.4453610252.74 86.223610259.8488.8936210277.5798.82027
10291.76100.630910305.95110.855710320.14119.067210359.15138.852910371.36143.2736
#Mann= 3 , 0 , 0
9586.715  0.0479       09586.715  0.0479       010371.36  0.0479       0
#XS Ineff= 2 , 0
       09906.436        10072.15       0
Bank Sta=9586.715,10371.36
Exp/Cntr=0.3,0.1

Type RM Length L Ch R = 1 ,4847.113,270.520400,270.520400,270.520400
XS GIS Cut Line= 6
1248222.92620441845381.8250097931248603.13453779845235.991676465
1248696.88453779845230.783343136 1248791.9366211845189.116676465
1248860.94703776845139.637509793 1249053.6553711845061.512509793
#Sta/Elev= 30
9545.90991.111989599.24485.993299627.35684.769139637.89785.27345 9694.1282.06758
9817.10677.520399841.70373.909049862.78673.945839880.35668.109999890.89867.04132
9908.46768.221739940.09276.646259967.22576.085969977.08374.320029993.51266.82077
10000.0865.2494610016.5170.6262810039.5176.2503810081.8275.6959310092.5774.73364
10157.8477.5011910207.0277.3814510259.47 80.209110301.95 84.257410333.8286.03393
10339.6687.9693710355.0696.5468510372.76101.689310397.54118.218210443.66 140.287
#Mann= 3 , 0 , 0
9545.909    0.12       09545.909    0.12       010443.66    0.12       0
#XS Ineff= 2 , 0
       09957.999        10121.99       0
Bank Sta=9545.909,10443.66
Exp/Cntr=0.3,0.1

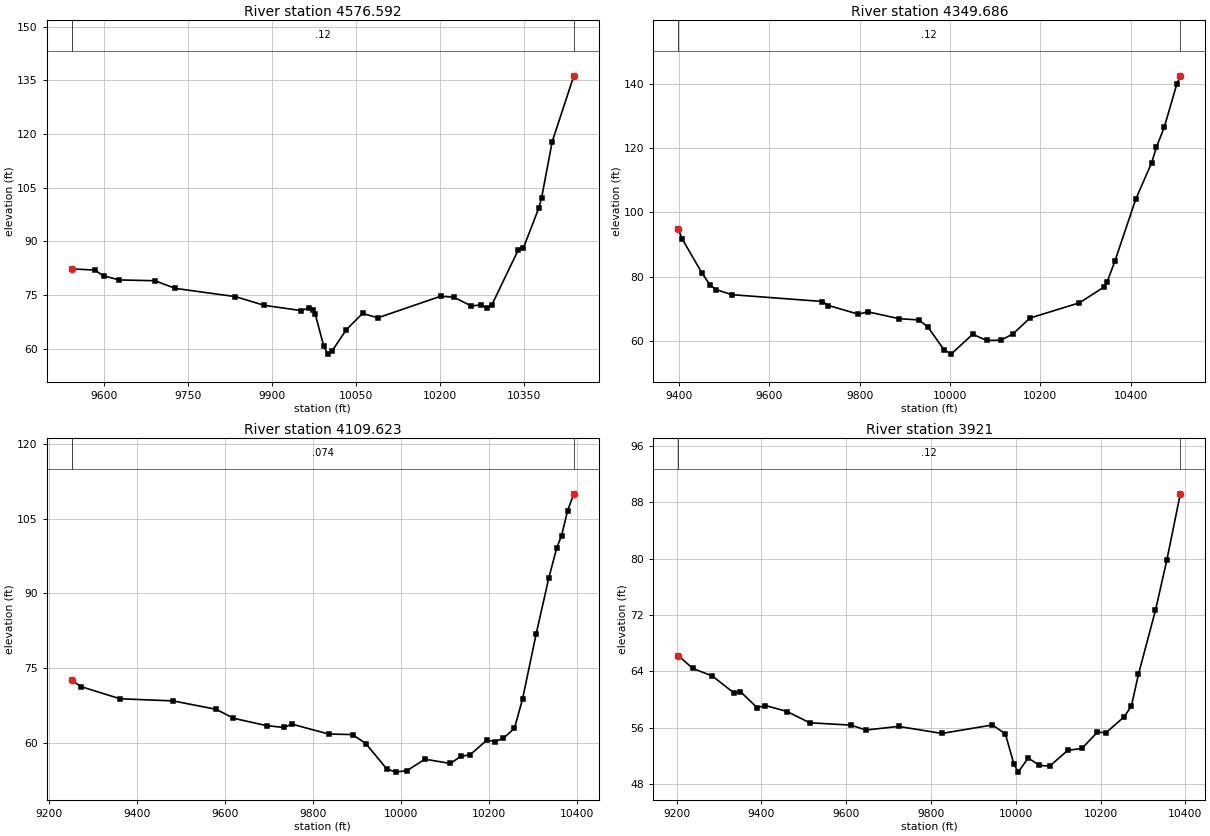
Type RM Length L Ch R = 1 ,4576.592,226.906400,226.906400,226.906400
XS GIS Cut Line= 5
1248545.84287107 845790.679176451248686.79056841845584.447255835
 1248850.5303711845251.6166764651248966.41578773845131.825009793
1249056.14482301845072.051800594
#Sta/Elev= 30
9543.28882.28122 9584.3881.956329599.99980.329469628.09379.206559691.67578.96788
9727.91876.837789835.06374.536399886.25272.109559952.06670.638529966.69271.40795
9974.00470.796879977.34769.661479992.28660.872249999.59958.4695310006.9159.21614
10032.5165.2369910061.7669.8556110088.8368.6093110201.21 74.652410224.8174.35313
10255.4671.9386610273.7272.2241710282.8571.4781410291.9872.1486910339.6987.66144
10348.6788.1891710376.26 99.383710381.11102.224310399.92117.8538 10438.5136.2322
#Mann= 3 , 0 , 0
9543.288    0.12       09543.288    0.12       0 10438.5    0.12       0
#XS Ineff= 2 , 0
       09823.499        10053.42       0
Bank Sta=9543.288,10438.5
Exp/Cntr=0.3,0.1

Type RM Length L Ch R = 1 ,4349.686,240.062800,240.062800,240.062800
XS GIS Cut Line= 6
1248588.20291265845973.4990132571248893.39646493845628.204230224
1249004.55086193845467.4758399711249064.62238811845369.061887901
1249100.00143406845299.6212886381249198.70451255845057.412232492
#Sta/Elev= 30
9398.676 94.68989407.82691.60175 9451.3981.055159468.86877.415539482.33775.95966
9517.10974.376359717.92972.247359731.03771.001979796.84568.328699818.942 69.0211
9887.266 66.90449930.65566.525769950.603 64.43599986.548 57.308910002.4955.88171
10050.2762.0452510081.6660.1269310112.7660.20763 10139.362.1514510177.0267.09559
10286.6171.84614 10340.476.6967910347.47 78.172610365.1784.8367610411.19104.0507
10446.36115.376310456.85120.193210474.33126.429810502.31139.969910509.86142.4295
#Mann= 3 , 0 , 0
9398.676    0.12       09398.676    0.12       010509.86    0.12       0
#XS Ineff= 2 , 0
       09856.423        10179.36       0
Bank Sta=9398.676,10509.86
Exp/Cntr=0.3,0.1

Type RM Length L Ch R = 1 ,4109.623,188.623100,188.623100,188.623100
XS GIS Cut Line= 6
1248616.54782006846124.2556683491248970.71448673845859.932751682
1249121.75615339845715.401501682 1249189.5151233845616.884429923
 1249256.7026233845508.5510965891249368.46477608845292.405263256
#Sta/Elev= 30
9252.313 72.50269274.33771.223769362.10168.811179482.39668.386199580.64866.69125
9619.91164.894129695.38763.404699734.33763.048479753.31863.701719836.15561.72636
9890.64661.610069920.79859.797819968.22154.714829988.49154.0610610014.5454.37476
10055.1756.6636710113.0855.8006710136.2457.2131510158.0857.5685910195.9560.50133
10214.41 60.208510232.8860.8271410258.7462.88017 10277.268.8160110308.0881.87626
10336.6593.0654110354.7799.1640110365.85101.647410379.51106.664910393.67110.0286
#Mann= 3 , 0 , 0
9252.313   0.074       09252.313   0.074       010393.67   0.074       0
#XS Ineff= 2 , 0
       09876.143        10171.37       0
Bank Sta=9252.313,10393.67
Exp/Cntr=0.3,0.1

Type RM Length L Ch R = 1 ,    3921,0.000000,0.000000,0.000000
XS GIS Cut Line= 6
1248813.58116558846317.6572693481249191.18533225845976.945463793
1249271.48047114845874.9489360151249316.68229946845805.588170381
1249337.42024087845716.6646683241249404.40871188 845351.30527282
#Sta/Elev= 30
9204.02566.26014 9238.1364.434489284.21463.358989336.07960.923319350.49861.14645
9390.26958.849019409.54159.169959460.97258.31683    951456.716659611.21756.38816
9646.56955.688539723.50856.202119825.83755.207799945.06456.408119975.41355.14346
9995.646  50.85910005.8149.7185310029.1751.7217510055.8650.6826610079.8750.56473
10122.5752.8110810155.92 53.075210192.6255.3970210212.6355.2986710255.9957.59159
10272.6759.0983110289.3563.6050510329.3772.6693110356.0679.7503310388.01  89.197
#Mann= 3 , 0 , 0
9204.025    0.12       09204.025    0.12       010388.01    0.12       0
#XS Ineff= 2 , 0
       09943.273        10174.44       0
Bank Sta=9204.025,10388.01
Exp/Cntr=0.3,0.1